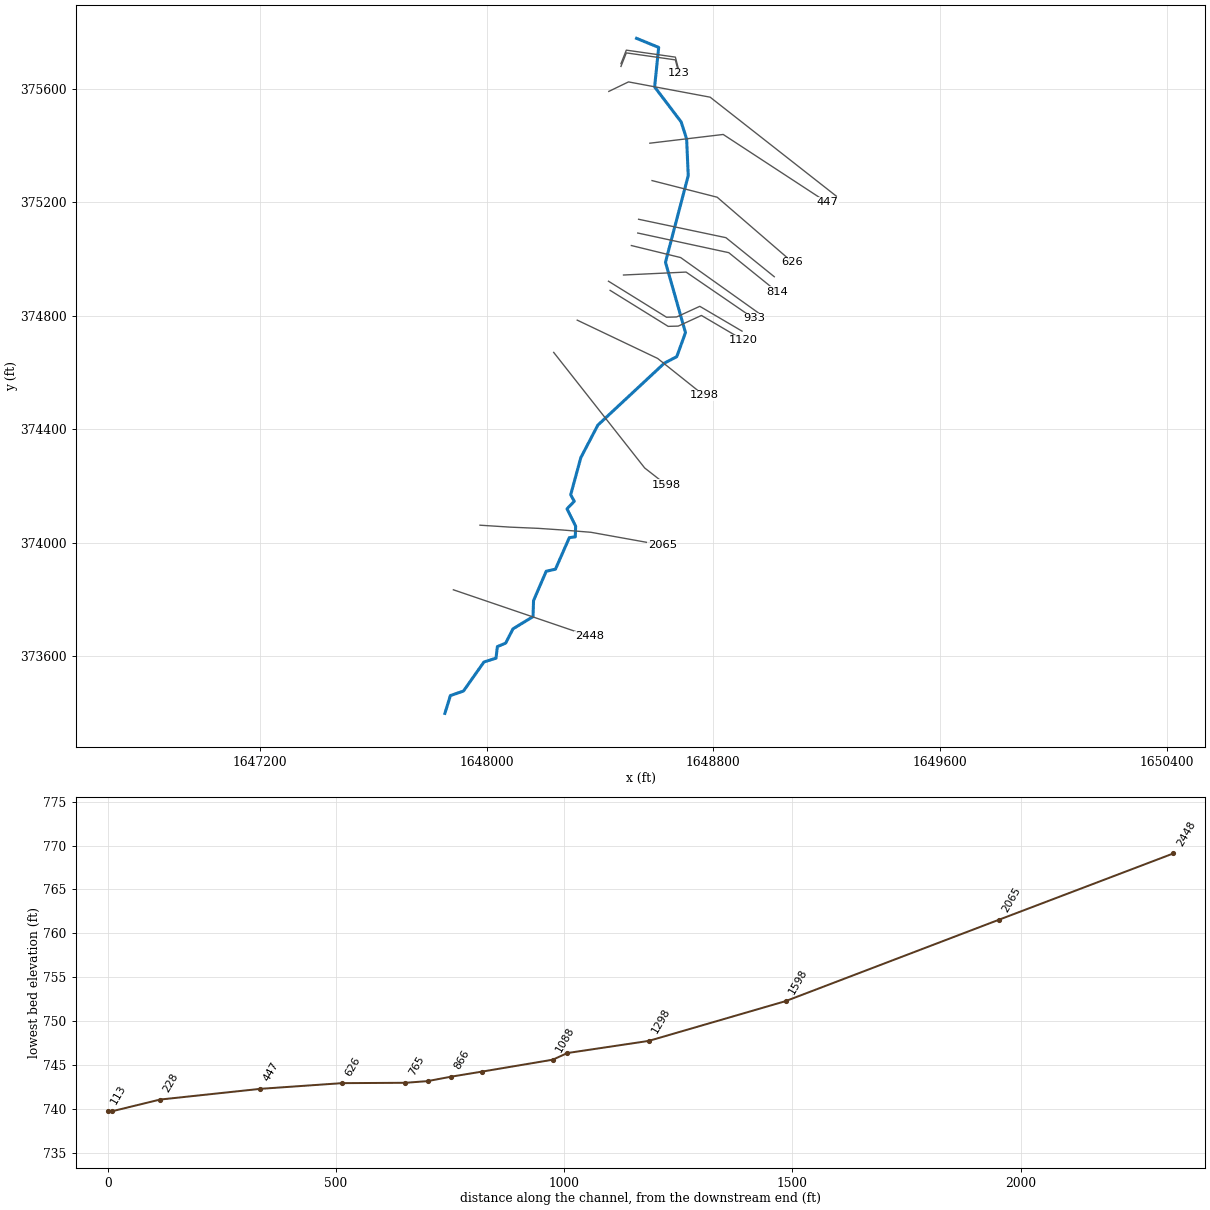
--- SFFSHGCKT1.prj (project) ---

Proj Title=SFFSHGCKT1
Current Plan=p01
Default Exp/Contr=0,0
English Units
Geom File=g01
Flow File=f01
Plan File=p01
BEGIN DESCRIPTION:
---------- MODELED AS PART OF WVEMD CTP PROGRAM, 2023----------
Stream Name: South Fork Fishing Creek Tributary 1
Flood Zone:  AFH
Wetzel County, WV
HEC-RAS Version: RAS 6.3
Vertical Datum: NAVD88
Projection: NAD 1983 StatePlane West Virginia S FIPS 4702 (US Feet)
Terrain: 1-meter West Virginia FEMA R3 South Central (collected 2018-2020)
Land Use: 2019 NLCD
Hydrologic Method:
WV 2010 Regional Regression Equations
Additional Model Notes:
None
END DESCRIPTION:
DSS Export Rating Curves= 0
DSS Export Rating Curve Sorted= 0
DSS Export Volume Flow Curves= 0
DXF OffsetX= 0
DXF OffsetY= 0
DXF ScaleX= 0
DXF ScaleY= 0

--- SFFSHGCKT1.p01 (plan) ---

Plan Title=Floodplain
Program Version=4.00
Geom File=g01
Flow File=f01
K Sum by GR=0
Std Step Tol=0.01
Critical Tol=0.01
Num of Std Step Trials=20
Max Error Tol=0.3
Flow Tol Ratio=0.001
Split Flow NTrial=30
Split Flow Tol=0.02
Split Flow Ratio=0.02
Log Output Level=0
Friction Slope Method=1
Unsteady Friction Slope Method=2
Unsteady Bridges Friction Slope Method=1
Global Log Level=0
CheckData=False
Run HTab=0
Run UNet=0
Run PostProcess=0
UNET Theta=0
UNET Theta Warmup=0
UNET ZTol=0
UNET ZSATol=0
UNET MxIter=0
UNET MaxInSteps=0
UNET DtIC=0
UNET DtMin=0
UNET MaxCRTS=0
UNET WFStab=0
UNET SFStab=0
UNET WFX=0
UNET SFX=0
UNET DSS MLevel=0
UNET DZMax Abort=0
UNET Convert EG Bridges=0
UNET Use Existing IB Tables=0
UNET Froude Limit=0
UNET Froude Power=0
Write IC File=0
Echo Input=False
Echo Output=False
Write Detailed=0

--- SFFSHGCKT1.f01 (steady flow) ---

Flow Title=Flow
Program Version=6.31
Number of Profiles= 1
Profile Names=F01pct
River Rch & RM=SFFSHGCKT1,Main            ,2448
     223
Boundary for River Rch & Prof#=SFFSHGCKT1,Main            , 1
Up Type= 0
Dn Type= 3
Dn Slope=0.00887
DSS Import GetInterval= 0
DSS Import GetPeak= 0
DSS Import FillOption= 0

--- SFFSHGCKT1.g01 (geometry) ---

Geom Title=Geometry
Program Version=6.31

River Reach=SFFSHGCKT1      ,Main
Reach XY= 30
1647852.50471296373398.1874101661647871.89610207373460.928098697
1647918.08779139 373476.959332051647990.44571413373579.369024431
1648032.99641147373592.8189574981648037.69384417373633.512582194
1648066.97877138373645.8907473061648092.79524481373696.150532331
1648163.58884055373739.179845345      1648165.38      373795.809
1648210.08243634373899.1902724031648242.68833468 373906.43602759
 1648291.5971822374017.5376071321648312.73063483374020.556671794
1648313.93826069374057.9930735961648283.44570761374119.280086224
1648309.10775723374145.8478552441648296.42768565374168.792746672
 1648332.2022101374299.6594572241648392.29555696374414.391790171
1648627.32007601374633.0423902081648670.79720629374655.602631222
1648701.58193439374740.5136192841648630.98806117374988.749476884
1648711.31960315375293.9855406211648705.62021637375423.061454355
1648686.29378507375483.3415138961648592.66717184375606.655299878
1648606.99286011375745.887559726     1648528.966      375777.928

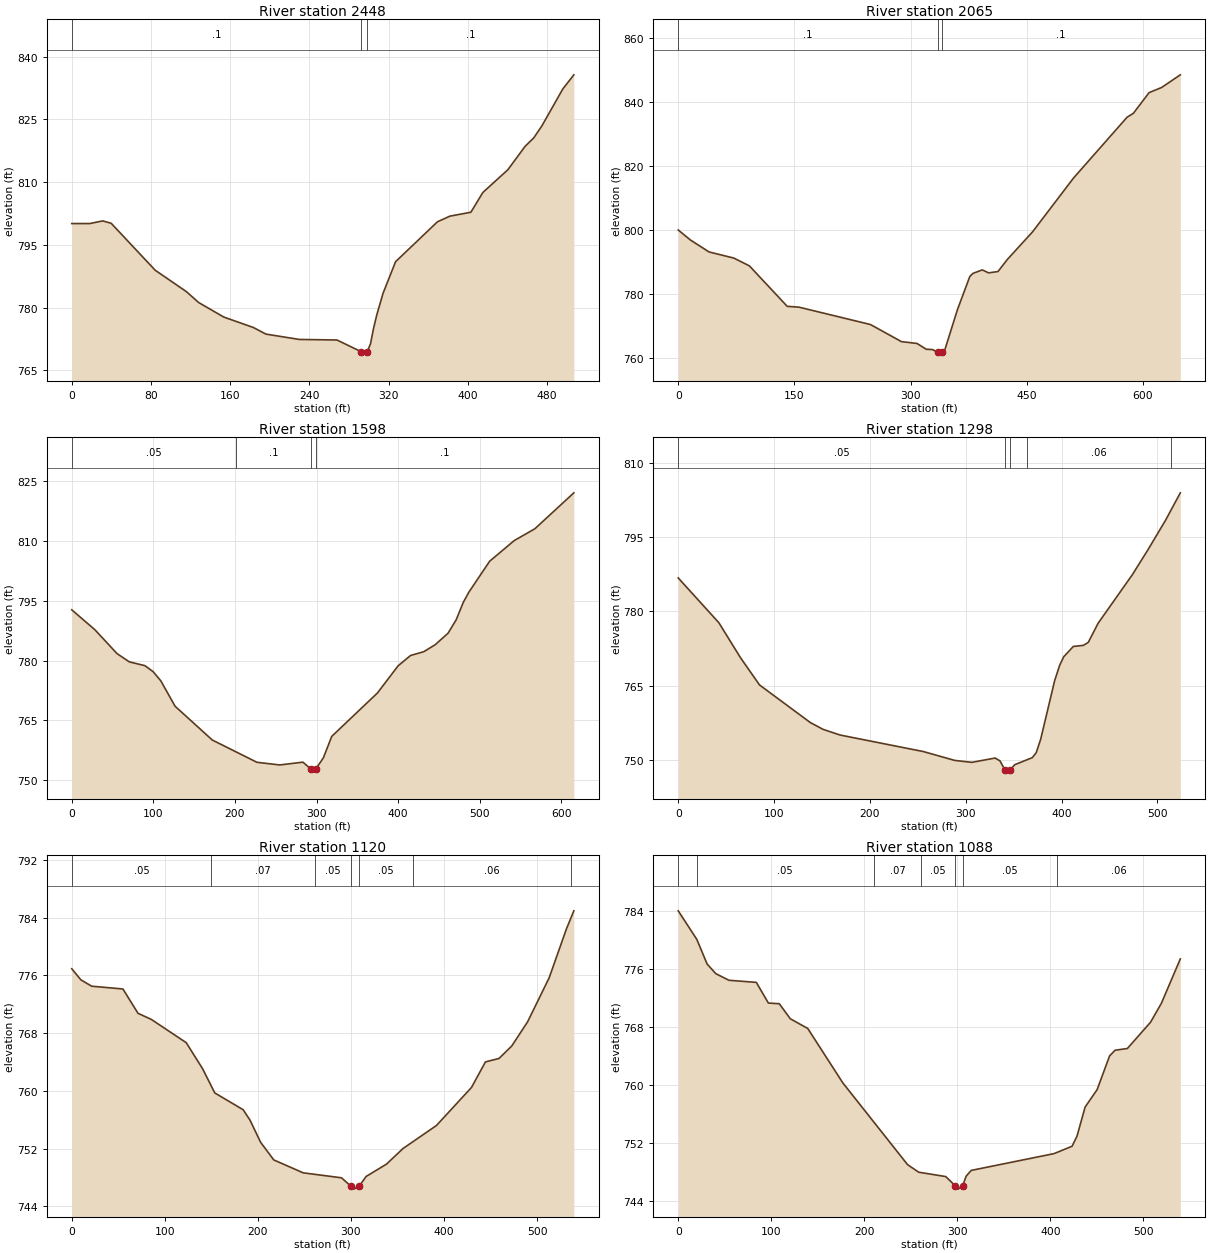
Type RM Length L Ch R = 1 ,2448    ,382.5,382.5,382.5
XS GIS Cut Line= 2
1647882.47929343373833.8831933251648362.55016575373670.331994339
#Sta/Elev= 30
       0  800.08    18.1  800.08    31.3  800.71    39.8  800.15    84.3  788.92
   115.8  783.81   128.2   781.2   153.6  777.73   183.4  775.24   196.1  773.66
   229.9  772.38   267.9  772.25   292.3  769.46   297.5  769.11  298.51769.4589
   301.8  771.36   304.9  775.07   308.1  778.22   314.4  783.37   327.1  790.96
   369.4   800.5     382  801.85   403.2  802.79   415.3  807.51   440.5  812.93
   458.1  818.58   466.6  820.52     475  823.46   496.1  832.27   507.2  835.63
#Mann= 3 ,-1,0
       0      .1       0   292.3    .045       0  298.51      .1       0
Bank Sta=292.3,298.51
XS Rating Curve= 0 ,0
Exp/Cntr(USF)=0,0
Exp/Cntr=0.3,0.1

Type RM Length L Ch R = 1 ,2065    ,467.4,467.4,467.4
XS GIS Cut Line= 6
1647976.36926951374061.5858364251648083.54818901374054.718396083
1648182.74484101 374050.42772226 1648264.5658716374044.869006336
1648367.57977317374036.6239440891648619.78497742373991.274953425
#Sta/Elev= 30
       0  799.98    15.8  796.85    39.8  793.13    71.9  791.21    91.9  788.78
   140.7  776.16     156  775.89   248.2  770.48   288.2  765.14   308.3  764.57
   320.3  762.76   328.4  762.66  335.32761.7559   336.4  761.55   340.6  761.76
   344.4   762.7   360.5   775.1   376.5  785.47   380.5  786.43   392.6  787.53
   400.7   786.6   412.9  787.02   425.1  790.82   457.6  799.43   510.4  816.19
   579.5  835.16   587.7   836.4     608  842.86   624.2  844.46   648.3  848.41
#Mann= 3 ,-1,0
       0      .1       0  335.32    .045       0   340.6      .1       0
Bank Sta=335.32,340.6
XS Rating Curve= 0 ,0
Exp/Cntr(USF)=0,0
Exp/Cntr=0.3,0.1

Type RM Length L Ch R = 1 ,1598    ,299.8,299.8,299.8
XS GIS Cut Line= 6
1648236.49703009374670.7263504271648294.52775392374597.095592171
1648395.11416693374469.4685508461648503.43809725 374332.02427192
1648557.60006243374263.3022965041648633.67996275374203.896247342
#Sta/Elev= 30
       0  792.76    28.3  787.77    55.4  781.79    70.5   779.7    89.6  778.75
    99.6  777.26   109.2  774.92   126.6  768.57   172.2  760.09   226.9   754.5
   254.8  753.83   283.3  754.53   293.1  752.79   296.6  752.28  299.01752.7869
   308.4  755.64   318.6     761   374.6  771.89     400  778.72   415.3  781.31
   431.3  782.24   445.3  783.99   461.2   786.9   471.1  790.26   479.8  794.63
   486.6  797.17   512.1  804.95   542.2  810.13   567.6  813.11   615.3  822.12
#Mann= 4 ,-1,0
       0     .05       0  201.25      .1       0   293.1    .045       0
  299.01      .1       0
Bank Sta=293.1,299.01
XS Rating Curve= 0 ,0
Exp/Cntr(USF)=0,0
Exp/Cntr=0.3,0.1

Type RM Length L Ch R = 1 ,1298    ,178,178,178
XS GIS Cut Line= 3
1648319.56107506374784.4585752021648603.30017089374649.469508643
1648767.22924798374518.886703798
#Sta/Elev= 30
       0  786.73    42.4  777.69      65  770.62    84.8  765.14   137.9  757.54
   151.2  756.17   168.9  755.03   255.5  751.71   288.5  749.91   306.3  749.52
   330.6  750.39   335.7  749.81   340.8  747.99   343.9  747.75  346.21747.9885
   351.1  749.05   369.5  750.48   373.5  751.48   378.1  754.16   392.7     766
     398  769.14   402.2  770.83   412.2  772.91   422.6  773.12   427.8  773.73
     438  777.57   473.8  787.39   489.5  792.24   508.3  798.33   523.8   803.9
#Mann= 5 ,-1,0
       0     .05       0   340.8    .045       0  346.21     .05       0
  364.21     .06       0  514.21      .1       0
Bank Sta=340.8,346.21
XS Rating Curve= 0 ,0
Exp/Cntr(USF)=0,0
Exp/Cntr=0.3,0.1

Type RM Length L Ch R = 1 ,1120    ,32.2,32.2,32.2
XS GIS Cut Line= 5
1648435.55563556 374889.490798871648640.47566723374762.498103187
1648676.07210466374763.4601690631648757.84770415374800.980738242
1648906.96791499374713.432743491
#Sta/Elev= 30
       0  776.93     9.8  775.39    21.4  774.51      55  774.12    71.2  770.75
    85.4  769.91     123  766.68   140.6  763.07   153.7  759.71   184.2  757.38
   191.6  755.93     203  752.86   217.1  750.42   248.7  748.63   289.9  747.94
  299.61746.8176   303.1  746.37  309.15746.8069   316.3  748.12   338.3  749.84
     356     752     392   755.2   429.6  760.47   444.6  764.01   459.2  764.49
   472.9  766.22   489.9  769.57   513.1  775.68   531.6  782.44   539.6  784.96
#Mann= 7 ,-1,0
       0     .05       0     150     .07       0  261.08     .05       0
  299.61    .045       0  309.15     .05       0  366.66     .06       0
  536.66      .1       0
Bank Sta=299.61,309.15
XS Rating Curve= 0 ,0
Exp/Cntr(USF)=0,0
Exp/Cntr=0.3,0.1

Type RM Length L Ch R = 1 ,1088    ,155.4,155.4,155.4
XS GIS Cut Line= 5
1648429.78324031374921.7200057291648634.70327198374794.727310046
 1648670.2997094374795.689375922 1648752.0753089374833.209945101
1648901.19551974 374745.66195035
#Sta/Elev= 30
       0  783.96      20  780.02      31  776.64    40.3  775.31    54.5  774.39
    83.9   774.1    96.9  771.25   108.6  771.16   120.4  769.09   139.2  767.75
   176.9  760.25   246.5  748.98   258.5  747.94   287.5  747.34   297.9  746.05
   300.7  745.61  305.55746.0407   309.5  747.41   314.9  748.19   403.8   750.5
   423.3  751.52   428.6  752.92   437.3  756.92   450.2  759.32   463.6  763.97
   469.5  764.75   482.7  764.99   507.5  768.59   519.2   771.2   539.6  777.33
#Mann= 7 ,-1,0
       0      .1       0      20     .05       0     210     .07       0
  261.08     .05       0   297.9    .045       0  305.55     .05       0
  406.66     .06       0
Bank Sta=297.9,305.55
XS Rating Curve= 0 ,0
Exp/Cntr(USF)=0,0
Exp/Cntr=0.3,0.1

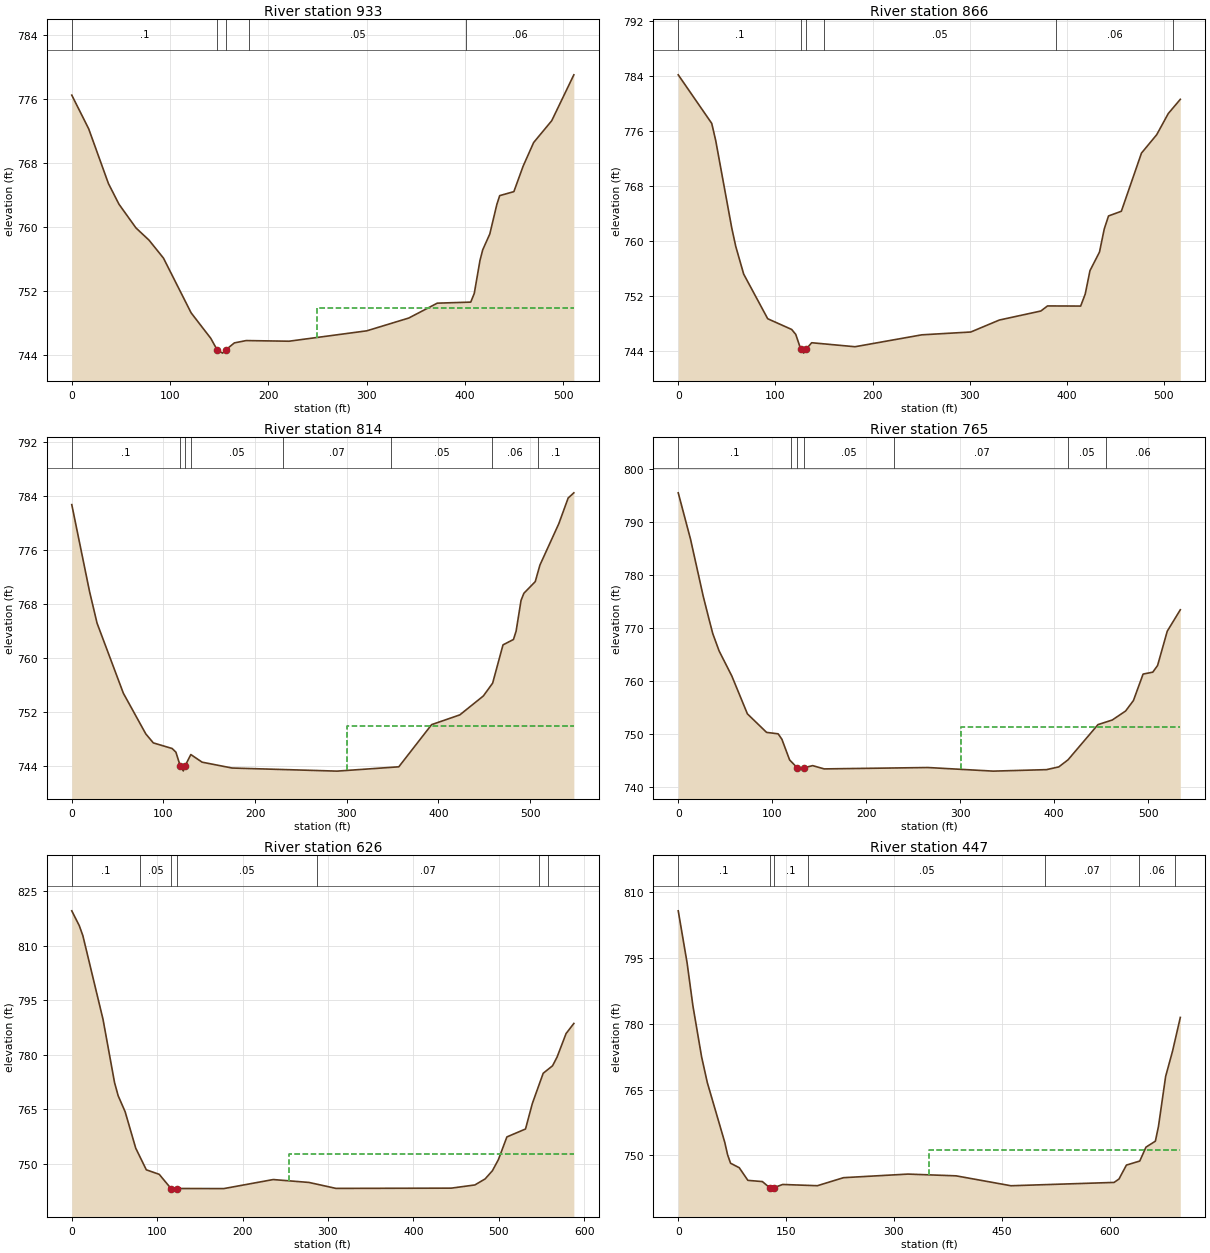
Type RM Length L Ch R = 1 ,933     ,67,67,67
XS GIS Cut Line= 3
1648482.88927668374943.5589011231648703.68339531374953.949212588
1648942.66055901374790.301807015
#Sta/Elev= 30
       0  776.52    17.2  772.31    37.3  765.46      48  762.88    65.3  759.91
    78.6  758.38    93.3  756.13   121.4  749.29   141.4   746.1  147.98744.6437
   153.4  744.25  156.67744.6588   165.4  745.53   177.4  745.82     221  745.74
   300.1  747.04   342.8  748.64   371.8   750.5   405.8  750.63   409.4  751.71
   415.2  755.83     418  757.17   425.2  759.15   432.4  762.86   435.3  763.95
   449.7  764.45   459.1  767.63   469.8  770.59   488.2  773.32   510.7  779.06
#Mann= 5 ,-1,0
       0      .1       0  147.98    .045       0  156.67      .1       0
     180     .05       0  401.04     .06       0
#XS Ineff= 2 , 0
                          249.12          749.85
Permanent Ineff=
       F       F
Bank Sta=147.98,156.67
XS Rating Curve= 0 ,0
Exp/Cntr(USF)=0,0
Exp/Cntr=0.3,0.1

Type RM Length L Ch R = 1 ,866     ,51.7,51.7,51.7
XS GIS Cut Line= 3
1648510.59677392375047.4620157731648684.63449096375005.034910624
1648959.97774478374809.350711367
#Sta/Elev= 30
       0  784.13    34.5  777.07    38.6  774.57    55.1  761.87    59.2   759.2
    67.4  755.16    92.1  748.68   116.8  747.12     121   746.4   126.2  744.23
   129.2  743.68  131.55744.2417   137.4  745.19     182  744.61   250.8  746.34
   301.2  746.75   330.6  748.49   373.3   749.8   380.2  750.54   414.3  750.52
     419  752.26   423.9  755.67   433.7  758.37   438.6  761.73     443  763.62
   456.2   764.3   476.9  772.75   492.6  775.43   504.5   778.5   516.9  780.57
#Mann= 6 ,-1,0
       0      .1       0   126.2    .045       0  131.55      .1       0
     150     .05       0  389.13     .06       0  509.13      .1       0
Bank Sta=126.2,131.55
XS Rating Curve= 0 ,0
Exp/Cntr(USF)=0,0
Exp/Cntr=0.3,0.1

Type RM Length L Ch R = 1 ,814     ,48.7,48.7,48.7
XS GIS Cut Line= 3
1648533.10911543375091.6208394991648854.34291156375022.352096399
1649024.91719144374884.680469488
#Sta/Elev= 30
       0  782.73    19.4  769.83    27.6  765.13    56.3  754.73    80.8  748.69
      89  747.36   109.5  746.53   113.6  745.99  118.41743.9222   121.7   743.2
  123.48743.9058   129.9  745.63   142.2   744.5   174.9  743.63   289.5  743.17
   356.8  743.81   392.6  750.07   423.4  751.52   449.1  754.33   459.2  756.23
   470.5  761.91   481.9  762.71   484.8  763.94   490.2  768.52   493.3  769.57
   505.7   771.3   510.8  773.76   531.4   779.9   541.6  783.71   547.8  784.48
#Mann= 8 ,-1,0
       0      .1       0  118.41    .045       0  123.48      .1       0
     130     .05       0     230     .07       0  348.62     .05       0
  458.62     .06       0  508.62      .1       0
#XS Ineff= 2 , 0
                             300          749.93
Permanent Ineff=
       F       F
Bank Sta=118.41,123.48
XS Rating Curve= 0 ,0
Exp/Cntr(USF)=0,0
Exp/Cntr=0.3,0.1

Type RM Length L Ch R = 1 ,765     ,138.7,138.7,138.7
XS GIS Cut Line= 3
1648536.13962294375140.1089596691648844.38552973375075.169513013
1649014.95980962374937.497886102
#Sta/Elev= 30
       0  795.57    13.1  786.79    26.6  776.02    32.7  771.73    36.8  768.94
    43.5  765.69      57  760.96    73.6   753.8      94   750.3   106.3  750.03
   110.3     749   118.5   745.1   126.7   743.6  133.72743.6013     143  744.02
   155.3   743.4   265.7  743.66   335.2  742.98   391.8  743.26   404.9  743.78
   414.7  745.11   446.6  751.77   461.8  752.64     476  754.34   484.3  756.31
   494.6  761.32   504.9  761.68     510  762.93   520.3  769.42   534.2  773.47
#Mann= 7 ,-1,0
       0      .1       0     120     .05       0   126.7    .045       0
  133.72     .05       0     230     .07       0  415.01     .05       0
  455.01     .06       0
#XS Ineff= 2 , 0
                          301.32          751.25
Permanent Ineff=
       F       F
Bank Sta=126.7,133.72
XS Rating Curve= 0 ,0
Exp/Cntr(USF)=0,0
Exp/Cntr=0.3,0.1

Type RM Length L Ch R = 1 ,626     ,179.2,179.2,179.2
XS GIS Cut Line= 3
1648583.54749754375276.4728896291648813.48124199 375217.78687117
1649079.01142388 374988.81519259
#Sta/Elev= 30
       0  819.65     8.8  815.56      13   812.8    36.6  789.73    50.1   772.3
    54.3   768.7    62.5  764.27    74.9  754.23    87.3  748.26   102.4  747.02
   116.2  743.11   120.3  742.94  123.29743.1107   178.1  743.09   235.9  745.58
   277.8  744.78   309.4  743.14   444.3  743.21     472  744.09     484  745.75
   492.5     748   499.6  751.09   509.5  757.33   531.3  759.51   539.3  766.54
     552  774.87     563  776.95   568.3  779.36   578.8  785.82   587.9  788.61
#Mann= 7 ,-1,0
       0      .1       0      80     .05       0   116.2    .045       0
  123.29     .05       0   287.3     .07       0   547.3     .06       0
   557.3      .1       0
#XS Ineff= 2 , 0
                          254.41          752.65
Permanent Ineff=
       F       F
Bank Sta=116.2,123.29
XS Rating Curve= 0 ,0
Exp/Cntr(USF)=0,0
Exp/Cntr=0.3,0.1

Type RM Length L Ch R = 1 ,447     ,219.6,219.6,219.6
XS GIS Cut Line= 3
1648575.85097053375408.2759146941648834.64669127375439.062022739
1649201.19379018375199.507619518
#Sta/Elev= 30
       0  805.77    12.3  793.93    20.4  784.12    32.5  772.47    40.5  766.56
    64.7  752.99    68.7  750.11    72.8   748.2    84.9  747.17    96.9  744.29
   117.1  744.01  127.41742.5912   129.2  742.29   132.6  742.59   145.3  743.35
   193.6  743.07   229.9   744.9   319.7  745.72   386.6  745.32   462.9  743.06
   606.4  743.82   613.2   744.6   623.5  747.77   642.1   748.7   650.7  751.86
   663.8  753.23   668.1  756.58   678.1     768   687.7  773.77   698.5  781.45
#Mann= 7 ,-1,0
       0      .1       0  127.41    .045       0   132.6      .1       0
     180     .05       0  510.62     .07       0  640.62     .06       0
  690.62      .1       0
#XS Ineff= 2 , 0
                          349.23          751.32
Permanent Ineff=
       F       F
Bank Sta=127.41,132.6
XS Rating Curve= 0 ,0
Exp/Cntr(USF)=0,0
Exp/Cntr=0.3,0.1

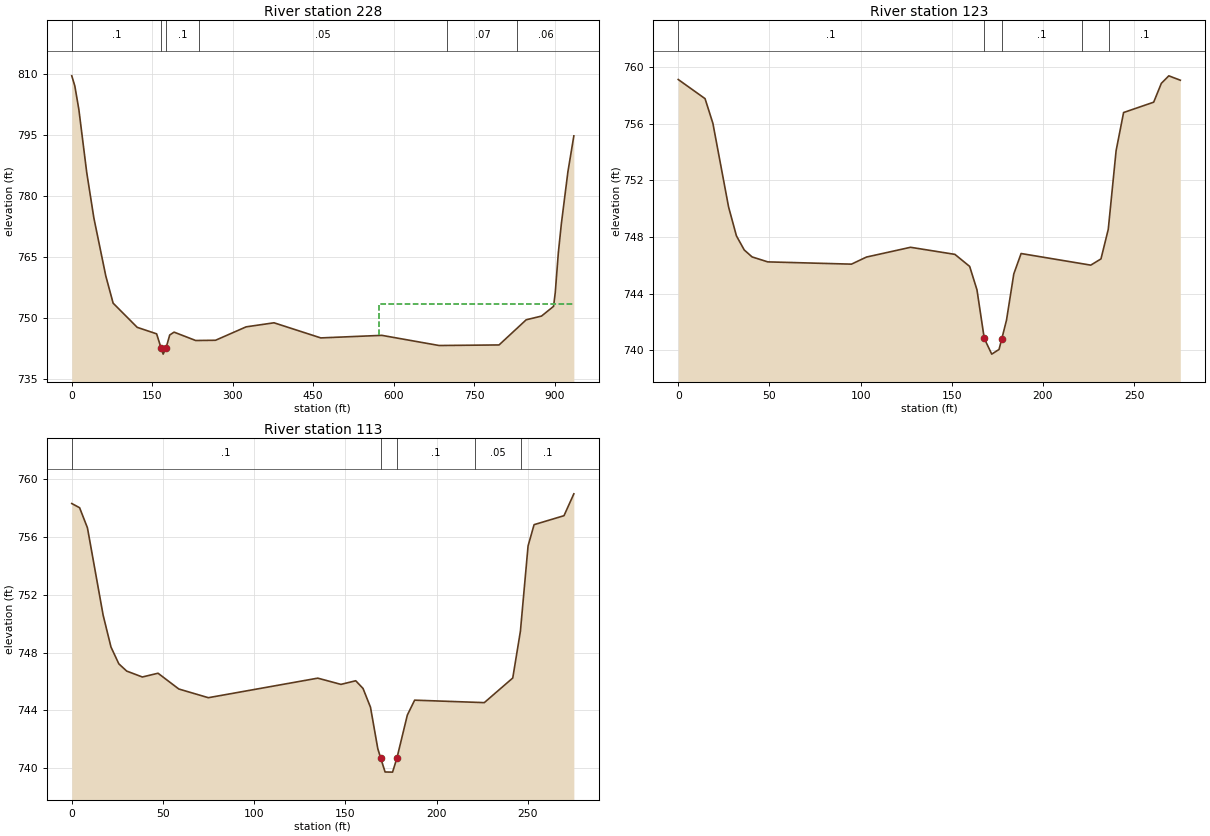
Type RM Length L Ch R = 1 ,228     ,104.9,104.9,104.9
XS GIS Cut Line= 4
1648430.99271152 375590.818294081648500.44694406375624.354112584
1648788.61408652375570.4636770561649233.90402997375221.635134675
#Sta/Elev= 30
       0  809.55     5.7  807.06    13.2  801.28    27.9  785.75    41.2  774.57
    63.4  760.32    77.1  753.61     122  747.66   158.2  746.06   166.3  742.64
   170.4  741.07  175.87742.6605   182.6  745.78   190.7  746.48     231  744.42
     268  744.48     325  747.78     377  748.78   464.2  745.06     578  745.69
   684.7  743.19   796.5  743.33   847.1  749.52   875.6  750.43   898.1  752.83
   901.3  756.27     907  766.03   912.7  773.22   924.8  785.91   935.9  794.77
#Mann= 6 ,-1,0
       0      .1       0   166.3    .045       0  175.87      .1       0
  237.13     .05       0  700.29     .07       0  830.29     .06       0
#XS Ineff= 2 , 0
                          572.69          753.38
Permanent Ineff=
       F       F
Bank Sta=166.3,175.87
XS Rating Curve= 0 ,0
Exp/Cntr(USF)=0,0
Exp/Cntr=0.3,0.1

Type RM Length L Ch R = 1 ,123     ,9.7,9.7,9.7
XS GIS Cut Line= 4
1648473.88793747375678.8780042241648492.78213514375726.616079712
1648665.86414242375702.0033890971648678.24398688375654.472923174
#Sta/Elev= 30
       0  759.12    14.7  757.77      19  756.03    27.6  750.13    31.9  748.09
    36.2  747.09    40.5   746.6    49.1  746.25      95  746.09   103.2  746.59
   127.4  747.28   151.7  746.78   159.8  745.93   163.8  744.28   167.8  740.85
   171.9  739.74   175.9  740.07  177.42740.8214     180  742.14     184   745.4
     188  746.84   226.2  746.02   231.8  746.46   235.8  748.55   240.1   754.1
   244.2  756.79   260.7  757.52   264.9  758.85     269  759.38   275.3  759.07
#Mann= 5 ,-1,0
       0      .1       0   167.8    .045       0  177.42      .1       0
  221.34     .05       0  236.16      .1       0
Bank Sta=167.8,177.42
XS Rating Curve= 0 ,0
Exp/Cntr(USF)=0,0
Exp/Cntr=0.3,0.1

Type RM Length L Ch R = 1 ,113     ,,,
XS GIS Cut Line= 4
1648473.92785358375688.5671620791648492.82205126375736.305237566
1648665.90405854375711.6925469521648678.28390299375664.162081028
#Sta/Elev= 30
       0  758.29     4.3     758     8.6  756.61    17.2  750.58    21.5  748.38
    25.8  747.22    30.1  746.72    38.7  746.31    47.3  746.57    58.7  745.48
    74.9  744.88   134.9  746.23   147.6   745.8   155.7  746.05   159.7  745.52
   163.8  744.22   167.8  741.36  169.34740.7321   171.8  739.75   175.9  739.74
  178.26740.6958     184  743.68     188  744.71   226.2  744.54   241.8  746.24
     246  749.47   250.2  755.36   253.5  756.83   269.9  757.45   275.3  758.96
#Mann= 5 ,-1,0
       0      .1       0  169.34    .045       0  178.26      .1       0
  221.34     .05       0  246.16      .1       0
Bank Sta=169.34,178.26
XS Rating Curve= 0 ,0
Exp/Cntr(USF)=0,0
Exp/Cntr=0.3,0.1
LCMann Table=0

Chan Stop Cuts=-1
Use User Specified Reach Order=0
Composite Channel Slope=5